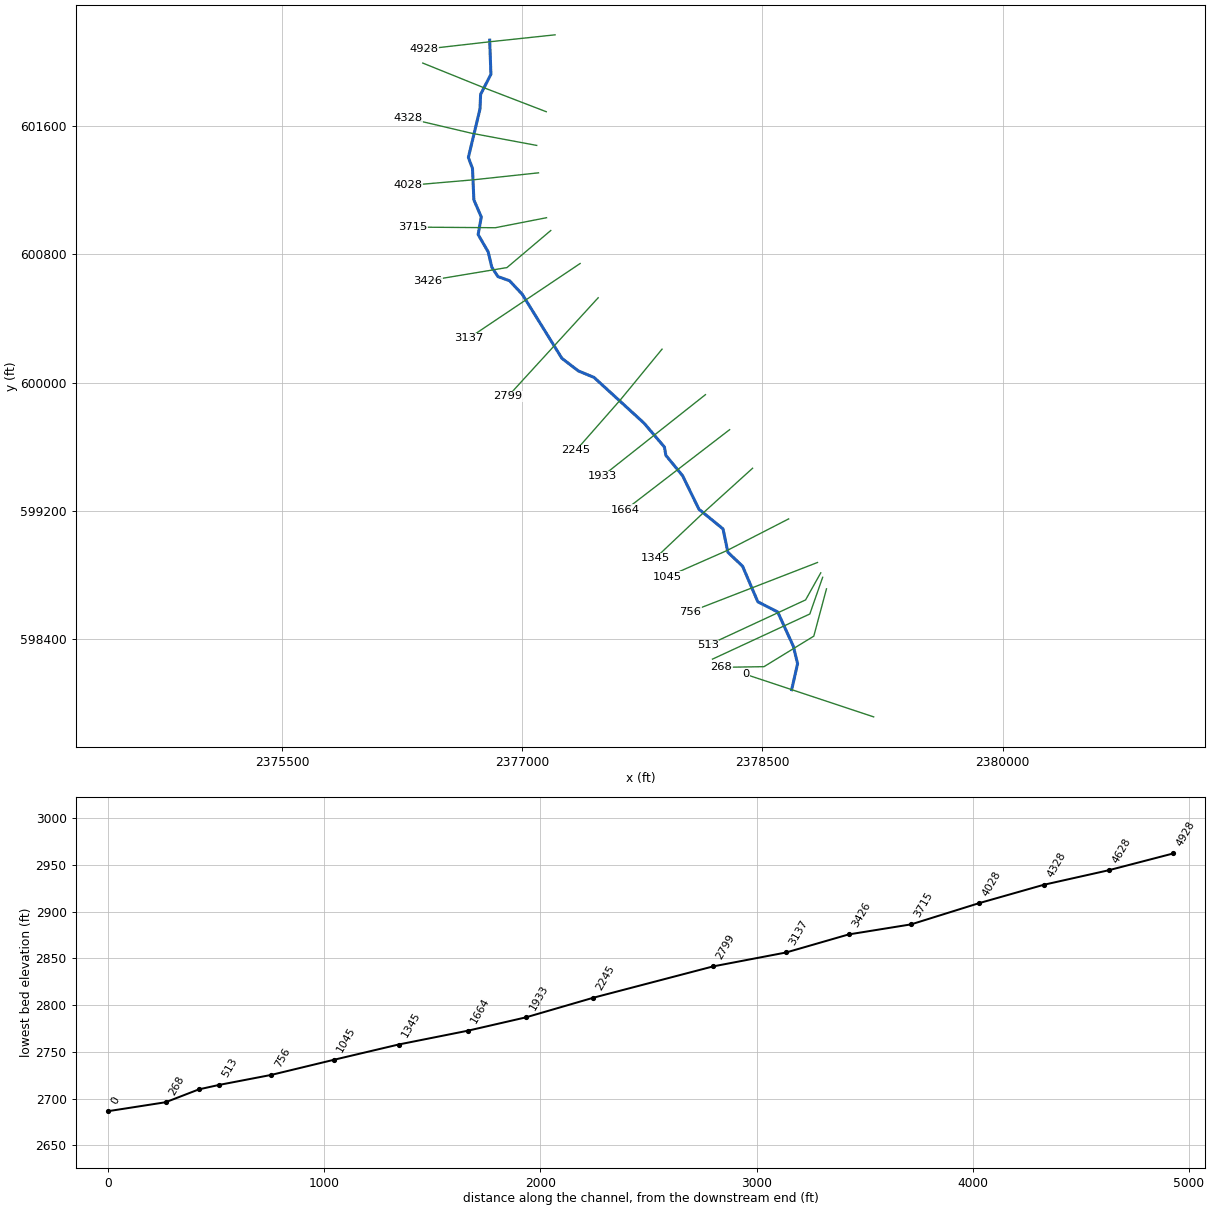
--- BACKRN.prj (project) ---

Proj Title=BACKRN
Current Plan=p01
Default Exp/Contr=0,0
English Units
Geom File=g01
Flow File=f01
Plan File=p01
BEGIN DESCRIPTION:
Stream Name: Back Run
Flood Zone: Approximate
Pendleton County, West Virginia
HEC-RAS Version: 5.0.7
Hydrology Method:
Regression equation
END DESCRIPTION:
DSS Export Rating Curves= 0
DSS Export Rating Curve Sorted= 0
DSS Export Volume Flow Curves= 0
DXF OffsetX= 0
DXF OffsetY= 0
DXF ScaleX= 0
DXF ScaleY= 0

--- BACKRN.p01 (plan) ---

Plan Title=Floodplain
Program Version=5.07
Short Identifier=Floodplain
Geom File=g01
Flow File=f01
Subcritical Flow
K Sum by GR= 0
Std Step Tol= 0.01
Critical Tol= 0.01
Num of Std Step Trials= 20
Max Error Tol= 0.3
Flow Tol Ratio= 0.001
Split Flow NTrial= 30
Split Flow Tol= 0.02
Split Flow Ratio= 0.02
Log Output Level= 0
Friction Slope Method= 1
Unsteady Friction Slope Method= 2
Unsteady Bridges Friction Slope Method= 1
Parabolic Critical Depth
Global Vel Dist= 0 , 0 , 0
Global Log Level= 0
CheckData=True
Encroach Param=-1 ,0,0, 0
Mapping Interval=1HOUR
Computation Time Step Use Courant=        0
Computation Time Step Use Time Series=    0
Computation Time Step Count To Double=0
Computation Time Step Max Doubling=0
Computation Time Step Max Halving=0
Computation Time Step Residence Courant=0
Run HTab= 0
Run UNet= 0
Run Sediment= 0
Run PostProcess= 0
Run WQNet= 0
Run RASMapper= 0
UNET Theta= 0
UNET Theta Warmup= 0
UNET ZTol= 0
UNET ZSATol= 0
UNET MxIter= 0
UNET Max Iter WO Improvement= 0
UNET MaxInSteps= 0
UNET DtIC= 0
UNET DtMin= 0
UNET MaxCRTS= 0
UNET WFStab= 0
UNET SFStab= 0
UNET WFX= 1
UNET SFX= 1
UNET 1D Methodology=Finite Difference
UNET DSS MLevel= 1
UNET Pardiso=0
UNET DZMax Abort= 0
UNET Use Existing IB Tables= 0
UNET Froude Reduction=False
UNET Froude Limit= 0
UNET Froude Power= 0
UNET D1 Cores= 0
UNET D2 Coriolis=0
UNET D2 Cores= 0
UNET D2 Theta= 1
UNET D2 Theta Warmup= 1
UNET D2 Z Tol= 0.01
UNET D2 Volume Tol= 0.01
UNET D2 Max Iterations= 20
UNET D2 Equation= 0
UNET D2 RampUpFraction=0.1
UNET D2 TimeSlices= 1
UNET D2 BCVolumeCheck=0
UNET D1D2 MaxIter= 0
UNET D1D2 ZTol=0.01
UNET D1D2 QTol=0.1
UNET D1D2 MinQTol=1
Write IC File= 0
Write IC File at Fixed DateTime=0
Write IC File at Sim End=0
Echo Input=False
Echo Parameters=False
Echo Output=False
Write Detailed= 0
HDF Write Warmup=0
HDF Write Time Slices=0
HDF Flush=0
HDF Face Node Velocities=0
HDF Compression= 1
HDF Chunk Size= 1
HDF Spatial Parts= 1
HDF Use Max Rows=0
HDF Fixed Rows= 1
Calibration Method= 0
Calibration Iterations= 20
Calibration Max Change=0.05
Calibration Tolerance=0.2
Calibration Maximum=1.5
Calibration Minimum=0.5
Calibration Optimization Method= 1
WQ AD Non Conservative
WQ ULTIMATE=-1
WQ Max Comp Step=1HOUR
WQ Output Interval=15MIN
WQ Output Selected Increments= 0
WQ Output face flow=0
WQ Output face velocity=0
WQ Output face area=0
WQ Output face dispersion=0
WQ Output cell volume=0
WQ Output cell surface area=0
WQ Output cell continuity=0
WQ Output cumulative cell continuity=0
WQ Output face conc=0
WQ Output face dconc_dx=0
WQ Output face courant=0
WQ Output face peclet=0
WQ Output face adv mass=0
WQ Output face disp mass=0
WQ Output cell mass=0
WQ Output cell source sink temp=0
WQ Output nsm pathways=0
WQ Output nsm derived pathways=0
WQ Output MaxMinRange=-1
WQ Daily Max Min Mean=-1
WQ Daily Range=0
WQ Daily Time=0
WQ Create Restart=0
WQ Fixed Restart=0
WQ System Summary=0
WQ Write To DSS=0
WQ Use Fixed Temperature=0
Sorting and Armoring Iterations= 10
XS Update Threshold= 0.02
Bed Roughness Predictor= 0
Hydraulics Update Threshold= 0.02
Energy Slope Method= 1
Volume Change Method= 1
Sediment Retention Method= 0
XS Weighting Method= 0
Number of US Weighted Cross Sections= 1
Number of DS Weighted Cross Sections= 1
Upstream XS Weight=0
Main XS Weight=1
Downstream XS Weight=0
Number of DS XS's Weighted with US Boundary= 1
Upstream Boundary Weight= 1
Weight of XSs Associated with US Boundary= 0
Number of US XS's Weighted with DS Boundary= 1
Downstream Boundary Weight= 0.5
Weight of XSs Associated with DS Boundary= 0.5
Percentile Method= 0
Sediment Output Level= 3
Mass or Volume Output= 0
Output Increment Type= 1
Profile and TS Output Increment= 1
XS Output Flag= 0
XS Output Increment= 10
Write Gradation File= 0
Read Gradation Hotstart= 0
Write HDF5 File= 1
Write Binary Output= 1
Write DSS Sediment File= 0
SV Curve= 0
Specific Gage Flag= 0

--- BACKRN.f01 (steady flow) ---

Flow Title=Flows
Program Version=5.07
Number of Profiles= 6
Profile Names=P100yr,P10yr,P25yr,P50yr,P500yr,P101yr
River Rch & RM=BACKRN,Main            ,4928
     586     274     387     484     859     713
River Rch & RM=BACKRN,Main            ,3426
     698     326     461     576    1025     849
River Rch & RM=BACKRN,Main            ,0
    1404     648     921    1156    2077    1709
Boundary for River Rch & Prof#=BACKRN,Main            , 1
Up Type= 0
Dn Type= 1
Dn Known WS=2690.52
Boundary for River Rch & Prof#=BACKRN,Main            , 2
Up Type= 0
Dn Type= 1
Dn Known WS=2689.05
Boundary for River Rch & Prof#=BACKRN,Main            , 3
Up Type= 0
Dn Type= 1
Dn Known WS=2689.62
Boundary for River Rch & Prof#=BACKRN,Main            , 4
Up Type= 0
Dn Type= 1
Dn Known WS=2690.06
Boundary for River Rch & Prof#=BACKRN,Main            , 5
Up Type= 0
Dn Type= 1
Dn Known WS=2691.52
Boundary for River Rch & Prof#=BACKRN,Main            , 6
Up Type= 0
Dn Type= 1
Dn Known WS=2690.98
DSS Import GetInterval= 0
DSS Import GetPeak= 0
DSS Import FillOption= 0

--- BACKRN.g01 (geometry) ---

Geom Title=Geometry
Program Version=5.07

River Reach=BACKRN          ,Main
Reach XY= 30
2376797.00700003602138.0429999982376804.79300001601925.149000004
2376740.49399999601799.907000005     2376736.498601708.137000009
2376664.01400003601405.9690000122376689.74200001601336.489000008
2376698.30899999601140.8170000172376744.71600002601033.966000021
     2376724.877600924.4819999932376787.77000001      600815.963
2376810.27430341 600720.593000012376848.42962205600661.798828095
2376921.21821746600635.7817269562377000.58500004600551.073000014
     2377247.847600151.489000008     2377351.426600072.347000018
2377448.30700004600032.3850000052377761.25299999      599746.456
2377888.26400003599597.1720000212377897.38800001599545.362000003
2378001.73500001599418.342999995     2378103.558599209.357999995
2378254.27599999 599086.108000012378284.27300003598940.653000012
2378376.47299999598852.9100000112378471.33300003598631.256000012
2378595.56099999598567.5150000162378692.90200004598354.189999998
      2378719.78598244.8690000182378682.92801034598082.459498689

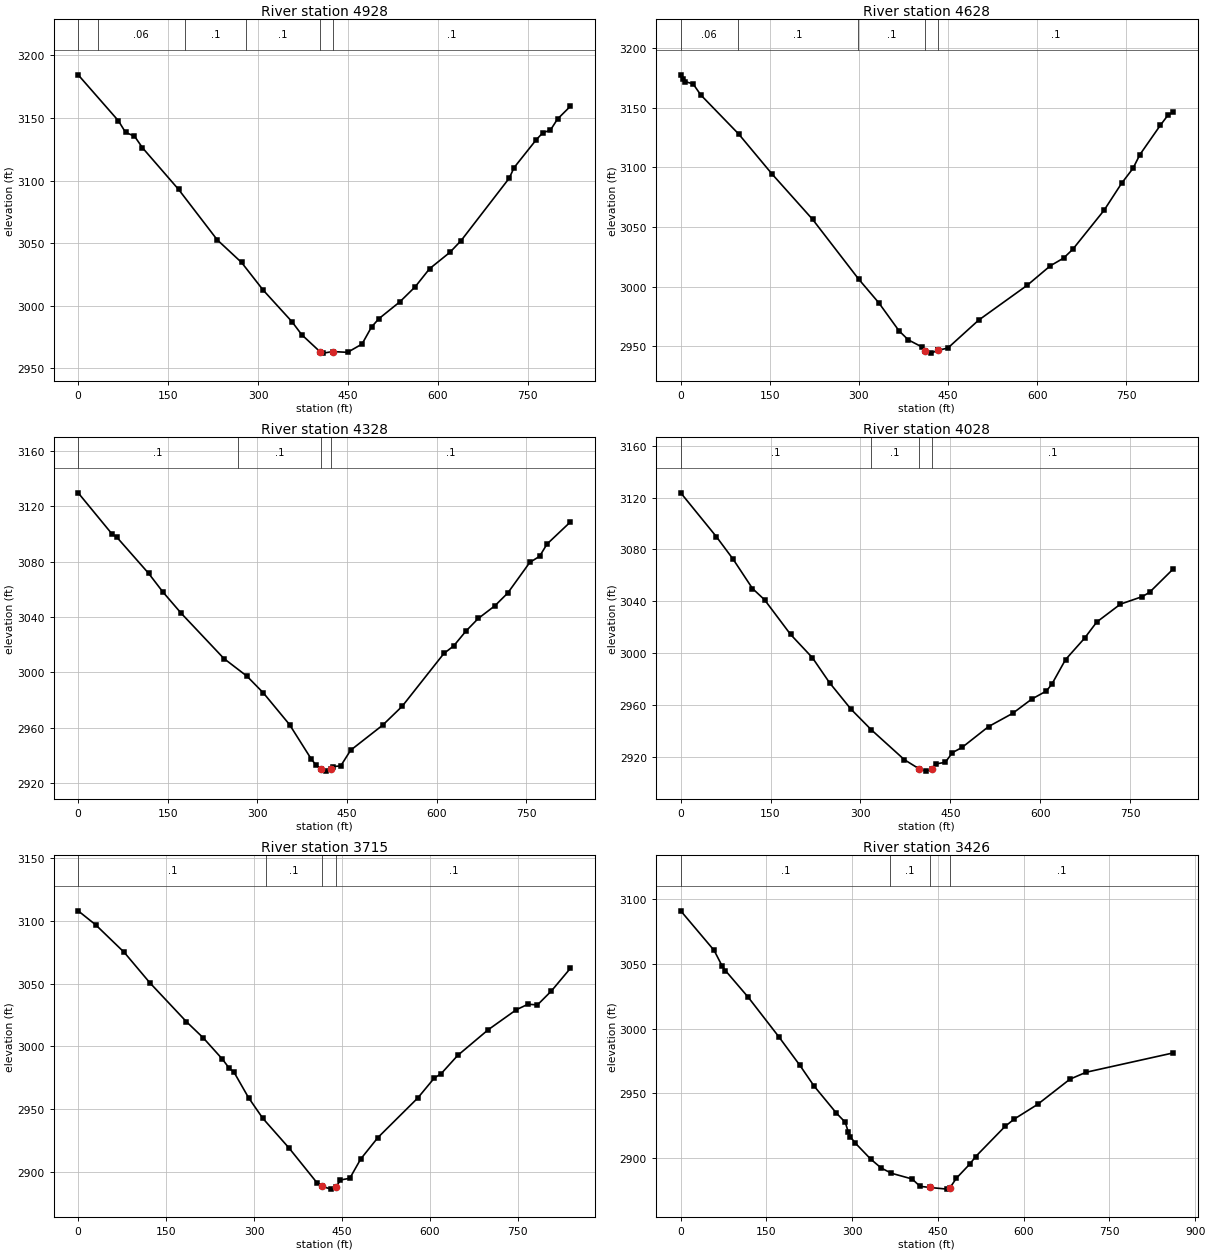
Type RM Length L Ch R = 1 ,4928    ,305.3,300,290.1
XS GIS Cut Line= 3
      2377205.44       602171.48     2376798.731      602128.199
     2376389.397      602081.494
#Sta/Elev= 30
       0 3184.42    67.1 3147.73    79.1  3138.4    93.9 3135.47   107.3 3126.14
   167.6 3092.84     232 3052.61   272.5 3034.57   308.4 3012.59   356.7  2987.2
   372.8 2976.92     403 2963.45     409 2962.16   424.6 2963.41   449.3 2962.79
   473.4 2969.39   489.3 2983.03   501.6 2989.68   536.7  3003.2     562 3015.09
   586.1 3029.57   619.8 3042.57   638.5 3051.92     719 3101.92     727  3110.3
   764.3 3132.77   775.4 3138.34   787.4 3140.09   799.5 3149.12     821 3159.34
#Mann= 6 ,-1 , 0
       0      .1       0   32.66     .06       0  177.45      .1       0
  280.41      .1       0     403    .045       0   424.6      .1       0
Bank Sta=403,424.6
XS Rating Curve= 0 ,0
Exp/Cntr=0.3,0.1

Type RM Length L Ch R = 1 ,4628    ,297.3,300,302.2
XS GIS Cut Line= 3
     2377150.228      601691.387     2376759.409      601841.734
     2376379.274       601995.11
#Sta/Elev= 30
       0 3177.78     3.7    3174       8    3172    20.9 3170.16    33.7 3160.93
    97.5 3128.12   153.7 3094.52   222.1 3056.37   299.4 3006.35   333.5 2986.34
   367.5 2962.85     383 2955.29   406.6 2949.16   411.22946.178   421.8 2944.12
   432.4 2946.43   432.4 2946.44   449.6 2948.34   501.4 2971.76   583.4 3001.12
   622.2 3017.43   644.5 3023.89   659.9 3031.23   712.8 3064.12   742.5 3086.93
   761.3 3099.19   773.1 3110.86   807.4  3135.4   820.6 3144.16   828.7 3146.39
#Mann= 5 ,-1 , 0
       0     .06       0   96.24      .1       0  299.19      .1       0
   411.2    .045       0   432.4      .1       0
Bank Sta=411.2,432.4
XS Rating Curve= 0 ,0
Exp/Cntr=0.3,0.1

Type RM Length L Ch R = 1 ,4328    ,294.9,300,303.4
XS GIS Cut Line= 3
      2377090.49      601480.933     2376682.256      601557.297
     2376284.555       601650.92
#Sta/Elev= 30
       0 3129.73    56.7 3099.96    64.9 3097.56   117.8 3071.59     142 3057.98
   172.4 3042.71   243.9 3009.99   282.6 2997.17     310  2985.1   353.8 2962.21
   390.4 2937.16   398.5 2932.75     406 2930.31   414.8 2928.59   422.82930.272
   427.1 2931.88   439.5 2932.39   456.1 2943.72   509.6 2961.79   542.2  2975.4
   612.1 3013.61   628.5 3019.08     649 3029.78   669.6 3038.91   697.4 3048.06
   718.9 3057.26   755.9 3079.44   772.3 3083.84   784.7  3092.7   823.9 3108.69
#Mann= 4 ,-1 , 0
       0      .1       0  267.63      .1       0     406    .045       0
   422.8      .1       0
Bank Sta=406,422.8
XS Rating Curve= 0 ,0
Exp/Cntr=0.3,0.1

Type RM Length L Ch R = 1 ,4028    ,313.3,312.9,311.2
XS GIS Cut Line= 3
     2377101.871      601309.745       2376694.6       601266.01
     2376284.063       601230.68
#Sta/Elev= 30
       0 3123.67    59.5 3089.84    87.6 3072.37   119.8 3049.81   139.9 3041.16
   183.4 3014.37   219.8 2996.43   248.5 2977.07   284.2 2956.71   317.9  2940.9
   373.3 2917.72   397.4 2910.82   409.5 2908.89   419.42910.708   425.5 2914.43
   441.6 2915.67   453.6  2923.2   469.7 2927.19   513.9 2943.28     554 2953.46
   585.9 2964.47   610.2 2970.67   619.4  2975.9   642.3 2994.94     674 3011.42
   694.5 3023.98     734 3037.76   770.8 3043.63   782.8 3046.99   821.7 3064.74
#Mann= 4 ,-1 , 0
       0      .1       0   317.9      .1       0   397.4    .045       0
   419.4      .1       0
Bank Sta=397.4,419.4
XS Rating Curve= 0 ,0
Exp/Cntr=0.3,0.1

Type RM Length L Ch R = 1 ,3715    ,284.5,289,286.1
XS GIS Cut Line= 3
     2377151.961      601029.3782376832.12029811600966.959087736
     2376318.386      600970.758
#Sta/Elev= 30
       0    3108    29.8 3096.88    78.7 3074.85   122.5 3050.55   184.6 3019.69
   213.2 3006.88   245.8 2989.97     258  2982.4   265.7 2979.53   290.6 2959.15
     315 2942.67   359.3 2919.24   407.3 2891.39     416 2888.47   431.3 2886.29
   440.2 2888.29   447.3 2893.58   463.3 2894.92     482 2910.34   511.3  2927.4
   579.3 2958.93   607.3 2974.73   619.3 2978.36   647.3 2992.79   699.3 3013.24
   747.3  3029.2   767.3  3033.6   783.3 3033.03   807.3 3044.23   839.6 3062.24
#Mann= 4 ,-1 , 0
       0      .1       0  321.05      .1       0     416    .045       0
   440.2      .1       0
Bank Sta=416,440.2
XS Rating Curve= 0 ,0
Exp/Cntr=0.3,0.1

Type RM Length L Ch R = 1 ,3426    ,283.4,288.8,308.1
XS GIS Cut Line= 3
     2377178.532      600949.5482376904.97461255600718.093654499
     2376408.969      600635.469
#Sta/Elev= 30
       0 3091.21    58.5 3060.51    72.2 3048.65    78.3 3044.84   118.1 3024.23
   171.3  2993.8   208.5 2971.45   233.2 2955.47   272.2 2934.52   287.9 2927.29
   293.1 2919.82   296.9 2915.95   305.4 2911.22   332.3 2898.82   350.8 2891.85
   368.7 2887.82   404.8 2883.39   418.7  2877.7   435.42876.824     466 2875.52
   471.32876.763   482.2 2883.94   505.6 2894.88     516 2900.76   567.4 2924.13
   583.6 2929.85   624.2 2941.15     681 2960.75   709.3 2966.11   861.2 2981.05
#Mann= 4 ,-1 , 0
       0      .1       0  366.68      .1       0   435.4    .045       0
   471.3      .1       0
Bank Sta=435.4,471.3
XS Rating Curve= 0 ,0
Exp/Cntr=0.3,0.1

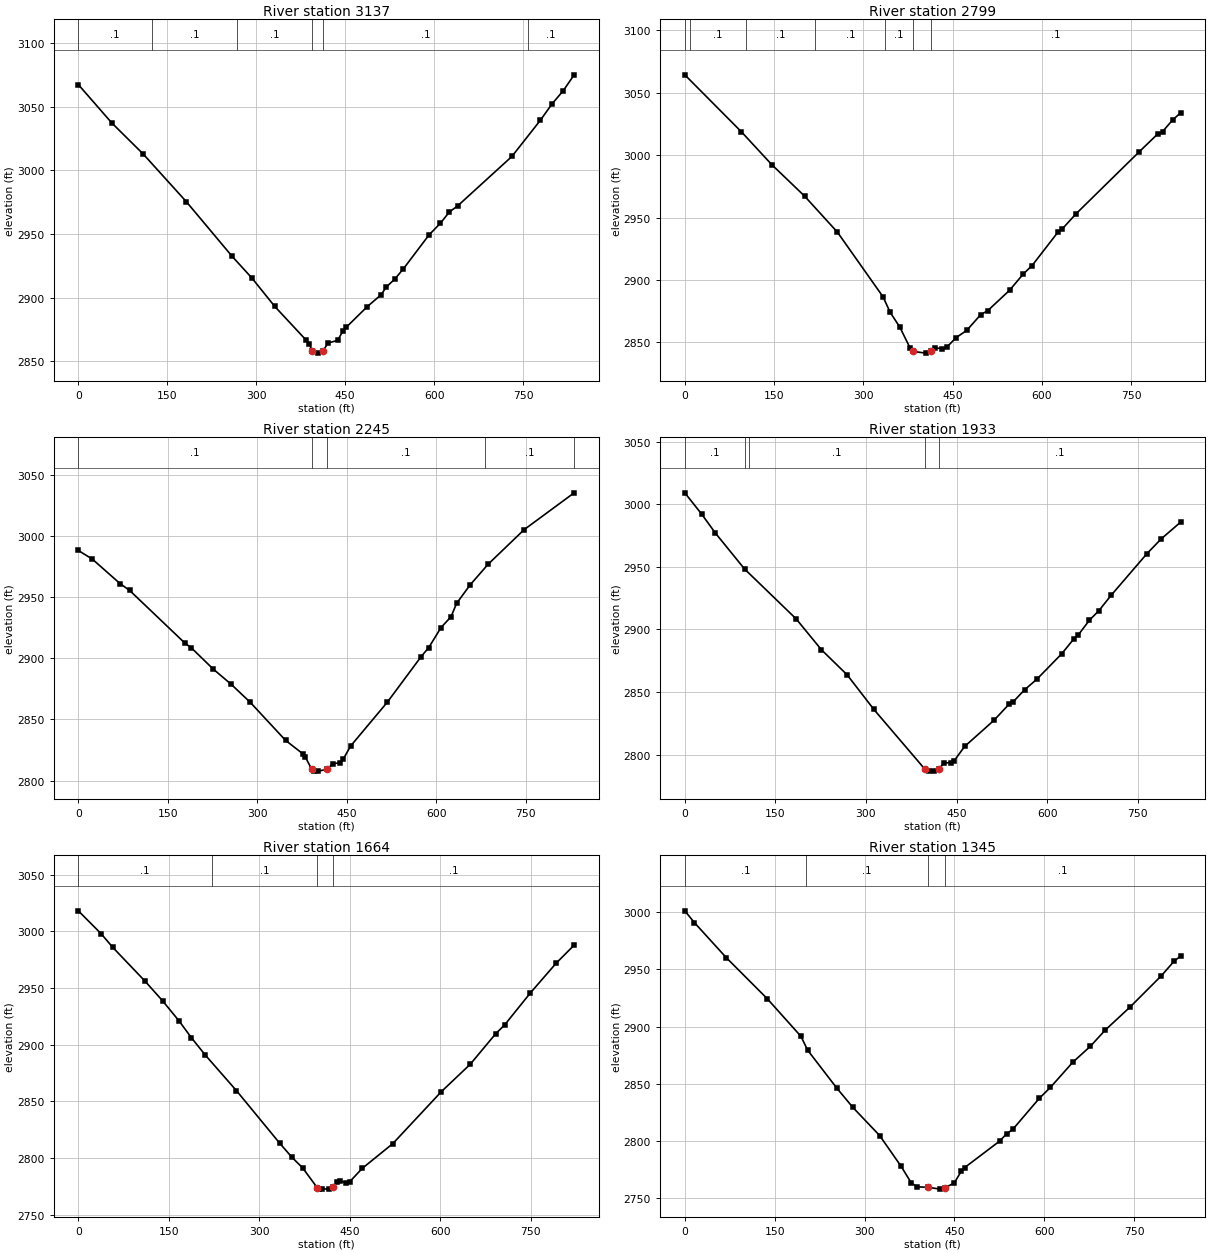
Type RM Length L Ch R = 1 ,3137    ,332.7,337.9,343.1
XS GIS Cut Line= 2
     2377361.783      600743.4552376667.58589209600277.726535703
#Sta/Elev= 30
       0  3067.5    56.6 3037.24   109.3 3012.91   181.9 2975.48   258.9  2932.6
   292.7  2915.3   331.2 2892.97   384.2 2866.41   388.9 2863.48   394.7 2858.08
   403.5 2856.24   413.1  2858.2   420.6 2864.08   437.2 2866.31   446.5 2873.93
   451.6 2876.52   486.9 2892.71   510.8 2902.29   519.1 2908.19   533.5 2914.45
     548  2922.5   591.3 2949.23   610.6 2958.48   625.6  2967.3   639.5 2972.04
     731 3010.96   779.2 3039.53   798.4 3052.13   817.7 3062.76     836 3075.18
#Mann= 6 ,-1 , 0
       0      .1       0  124.29      .1       0  268.13      .1       0
   394.7    .045       0   413.1      .1       0  758.45      .1       0
Bank Sta=394.7,413.1
XS Rating Curve= 0 ,0
Exp/Cntr=0.3,0.1

Type RM Length L Ch R = 1 ,2799    ,552.2,554.4,553.2
XS GIS Cut Line= 2
2377474.53813707600529.5329619162376912.00913707599914.772961916
#Sta/Elev= 30
       0 3064.41    95.2 3018.71   146.1 2992.46   201.2 2967.25   256.5 2938.29
     333  2886.6   345.2    2874   361.3 2862.24   378.9  2845.2   383.9 2842.74
   404.8 2841.34   414.5 2842.81   421.1 2845.46   432.1 2845.02   440.6 2846.24
   455.9 2853.74   473.7  2859.5   497.4 2872.21   509.3 2875.44   545.8 2891.71
   568.5 2904.58   583.7 2911.55   627.4 2938.48   633.7 2940.52   657.4 2952.96
   762.6 3002.21   794.5 3016.87     803 3018.96   819.9 3028.26   833.3 3033.93
#Mann= 7 ,-1 , 0
       0      .1       0    8.02      .1       0  102.41      .1       0
  219.53      .1       0  336.66      .1       0   383.9    .045       0
   414.5      .1       0
Bank Sta=383.9,414.5
XS Rating Curve= 0 ,0
Exp/Cntr=0.3,0.1

Type RM Length L Ch R = 1 ,2245    ,314.8,311.8,308.4
XS GIS Cut Line= 3
     2377873.498      600208.977     2377615.502      599894.608
      2377335.51        599575.9
#Sta/Elev= 30
       0  2988.1    23.4 2981.09      70 2961.01    85.9  2955.5   178.6  2912.4
     189 2908.75     226 2891.22   256.3  2878.7   288.1 2864.03   347.3 2832.94
   375.8 2822.13   380.4 2819.31   390.8 2809.65   395.6 2807.95   401.1 2807.81
     417 2809.21     426 2813.86   438.2  2814.6   443.6 2817.32   456.3 2828.32
   517.6 2864.01   574.2 2901.19   587.3 2908.83   607.8 2925.11   624.6 2933.99
   633.8 2944.82   656.4 2959.89   686.6 2976.81   747.1 3005.14   830.9 3035.22
#Mann= 5 ,-1 , 0
       0      .1       0   390.8    .045       0     417      .1       0
  681.24      .1       0  830.16      .1       0
Bank Sta=390.8,417
XS Rating Curve= 0 ,0
Exp/Cntr=0.3,0.1

Type RM Length L Ch R = 1 ,1933    ,267,268.9,267.3
XS GIS Cut Line= 2
     2378144.293      599924.473     2377500.407      599414.865
#Sta/Elev= 30
       0 3009.04    27.9 2992.07    50.6 2976.95      99 2948.21   184.5 2908.35
   226.4 2883.69   268.9  2863.7   313.1 2836.11     398 2788.19   403.7 2786.95
   412.3 2786.83   420.3 2788.41   429.4 2793.31   440.7 2793.63   445.8 2794.88
   463.5 2806.53   512.1 2827.42   537.5  2840.5     544 2842.25   563.1 2851.91
   583.1 2860.22   624.3 2880.54   644.7 2892.65   651.5 2895.47   670.2 2907.35
   685.8 2914.93   705.9  2927.1   765.4 2960.47   788.9 2972.21   821.2 2985.64
#Mann= 5 ,-1 , 0
       0      .1       0   99.51      .1       0   106.2      .1       0
     398    .045       0   420.3      .1       0
Bank Sta=398,420.3
XS Rating Curve= 0 ,0
Exp/Cntr=0.3,0.1

Type RM Length L Ch R = 1 ,1664    ,317.1,319.3,321.1
XS GIS Cut Line= 2
     2378295.208      599705.784     2377643.515      599204.599
#Sta/Elev= 30
       0 3018.23    37.6 2998.13    57.2  2985.9   110.8 2956.01   139.7 2938.78
   167.1 2920.97   187.3  2906.3   210.6 2890.83     262 2859.58   333.6 2813.24
   353.8 2800.86   372.2  2791.1     396 2773.86   398.9 2772.73   404.3 2772.53
     416 2772.78   421.7  2774.2   429.5 2778.73   433.1 2779.88   444.5 2778.18
   449.7 2778.89   470.6 2790.78   521.5 2812.75   601.8 2858.54   649.9 2882.82
   691.9 2909.66   706.8 2917.48   749.7 2945.87   792.1  2971.9   822.1 2987.97
#Mann= 4 ,-1 , 0
       0      .1       0  221.63      .1       0     396    .045       0
   421.7      .1       0
Bank Sta=396,421.7
XS Rating Curve= 0 ,0
Exp/Cntr=0.3,0.1

Type RM Length L Ch R = 1 ,1345    ,303.6,300,291.4
XS GIS Cut Line= 3
      2378438.72      599464.997     2378127.806       599183.73
     2377831.343      598903.254
#Sta/Elev= 30
       0 3001.26    16.1  2990.9    69.4  2960.2   137.4 2924.49   193.9 2891.42
   204.9 2879.43   253.5 2846.28   280.4 2829.33   325.1 2804.71   360.9 2777.82
   378.1 2763.09   388.3  2759.8   406.4 2759.39   426.2 2757.81   434.8 2759.23
   449.6 2763.15   461.2 2773.34     467 2776.66   525.3 2799.78   536.9 2806.16
   547.4 2810.13   591.4 2837.14   610.2 2846.85   647.5 2868.84   676.6 2882.66
   701.5 2896.89   743.2 2917.17   795.2 2944.43   816.7 2957.32   827.4 2961.68
#Mann= 4 ,-1 , 0
       0      .1       0   201.8      .1       0   406.4    .045       0
   434.8      .1       0
Bank Sta=406.4,434.8
XS Rating Curve= 0 ,0
Exp/Cntr=0.3,0.1

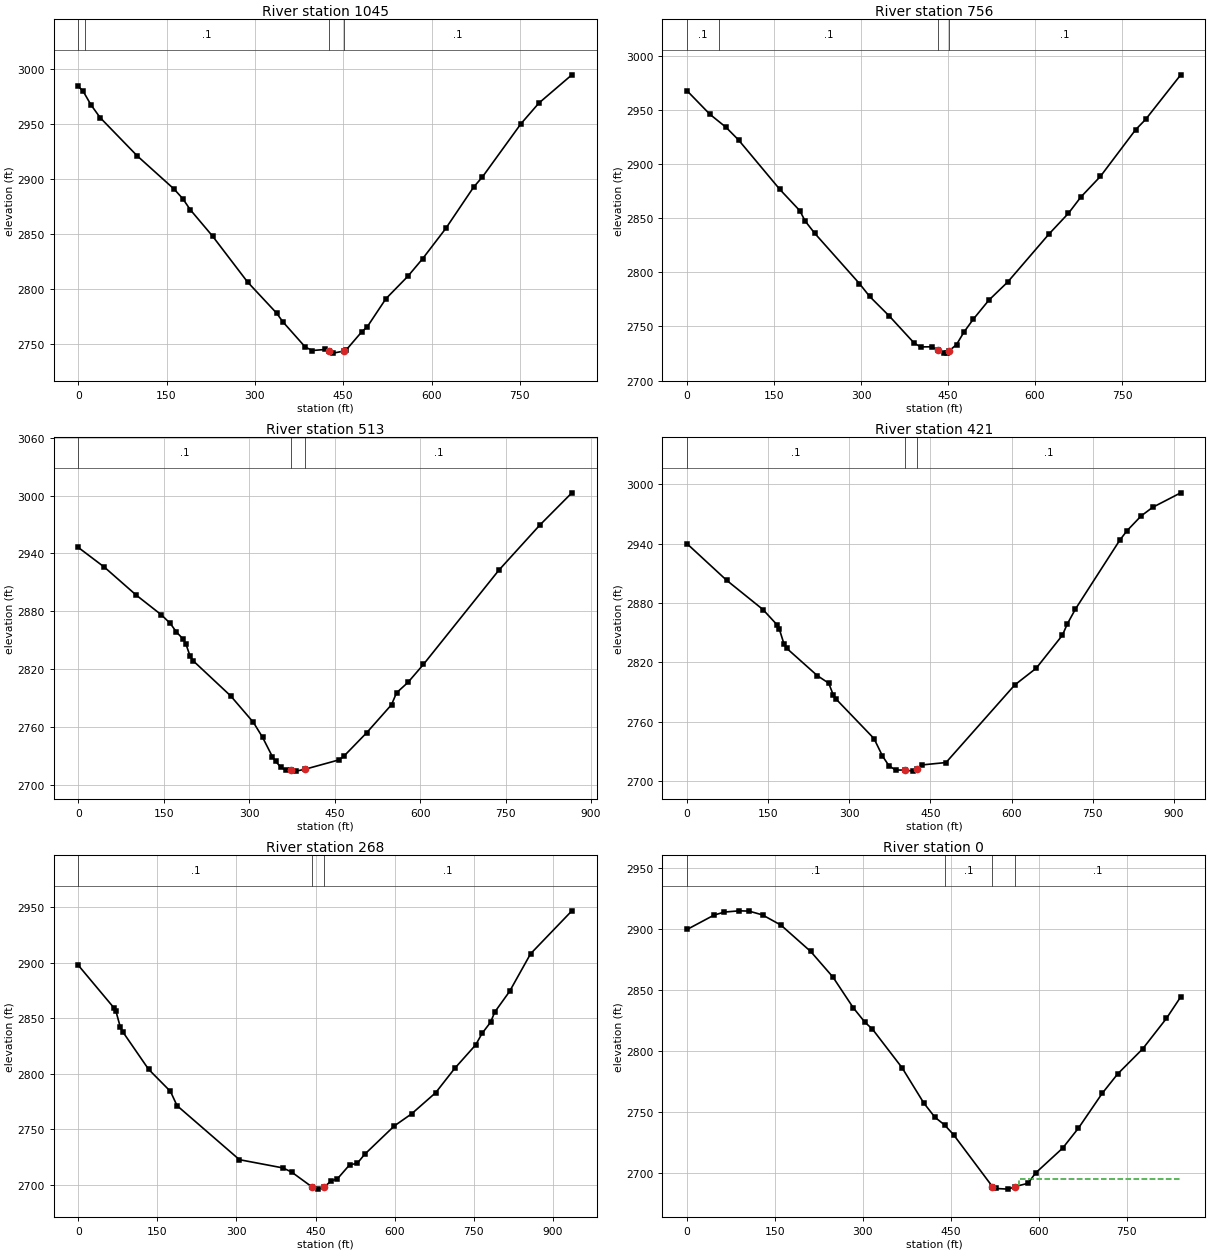
Type RM Length L Ch R = 1 ,1045    ,290,288.7,288.9
XS GIS Cut Line= 3
     2378663.966      599148.714     2378278.689      598950.918
     2377907.746      598787.687
#Sta/Elev= 30
       0 2983.77     8.2 2979.53    21.5 2967.11    37.3 2955.33   100.2 2920.65
   162.7 2890.53   177.6 2881.76   190.2  2871.8   228.1 2847.77   287.5 2806.11
   336.8 2777.86   347.6 2769.86   385.5 2747.01   397.4  2743.8   419.5 2744.76
   425.62743.255   433.1 2741.44   451.3 2743.34   454.9 2744.21   481.6 2760.85
   490.7 2765.21   522.5 2790.83   559.8 2811.23   584.8 2827.13   624.3 2854.76
   671.5 2892.23   686.5 2901.51     752  2949.9   782.6 2968.73   838.4 2994.28
#Mann= 4 ,-1 , 0
       0      .1       0   11.25      .1       0   425.6    .045       0
   451.3      .1       0
Bank Sta=425.6,451.3
XS Rating Curve= 0 ,0
Exp/Cntr=0.3,0.1

Type RM Length L Ch R = 1 ,756     ,241.8,243.7,241.3
XS GIS Cut Line= 2
2378843.95570392598876.470012097     2378050.352      598568.793
#Sta/Elev= 30
       0  2967.9    39.3 2946.21    67.1 2934.18    88.7 2922.47     160 2876.69
   194.4 2857.03   203.5 2847.54   220.1 2836.13   297.3 2789.56   314.6 2777.86
   348.8 2759.55   391.7 2734.53   402.7 2731.08   422.6 2731.17   432.32727.804
   443.2 2725.32   447.5 2725.55   451.8 2727.35   464.6 2733.25   477.5 2744.84
   493.7 2756.81   520.4 2774.31   552.9 2791.11     624 2835.44   657.6 2854.64
   679.1 2869.75   712.6 2888.68   773.5 2931.98   790.7 2941.48   851.2 2982.68
#Mann= 4 ,-1 , 0
       0      .1       0   55.11      .1       0   432.3    .045       0
   451.8      .1       0
Bank Sta=432.3,451.8
XS Rating Curve= 0 ,0
Exp/Cntr=0.3,0.1

Type RM Length L Ch R = 1 ,513     ,91.4,91.2,91.7
XS GIS Cut Line= 3
2378864.46979758598811.8621560662378769.77163541598642.843917261
2378159.62778043598359.948141672
#Sta/Elev= 30
       0 2946.28    46.1  2925.7   101.7 2896.87     146 2876.36   161.6 2867.46
   172.4 2858.54   184.5 2851.06   189.1 2845.98     196 2834.09   201.5 2828.91
   267.6 2792.39   307.3 2765.09   323.4 2749.65   340.6 2729.64   346.6 2724.52
   355.6 2718.51   364.6 2715.28   373.4 2716.18   382.3  2714.5   397.8 2716.42
   457.2 2726.08     466 2729.84   506.3 2754.34   549.8 2783.31   558.6 2795.65
   578.6 2806.38   605.7 2824.96   738.2 2922.69   809.9  2969.3   866.3  3002.8
#Mann= 3 ,-1 , 0
       0      .1       0   373.4    .045       0   397.8      .1       0
Bank Sta=373.4,397.8
XS Rating Curve= 0 ,0
Exp/Cntr(USF)=0,0
Exp/Cntr=0.3,0.1

Type RM Length L Ch R = 1 ,421     ,151.3,153.8,158.1
XS GIS Cut Line= 3
2378876.29441874598783.9075497142378796.22111346598554.965564204
2378188.34066918598273.017306186
#Sta/Elev= 30
       0 2939.76    73.1 2902.85   140.2 2873.28   166.3 2857.83   170.6 2853.33
   179.1 2838.54   184.1 2834.09   240.6 2806.49   261.8 2798.77   270.6 2786.45
     275 2782.94   345.6 2742.75   361.2 2725.15   373.2 2715.28   385.3    2711
   402.9 2710.85   418.4 2709.84     425 2711.54   433.8 2716.08   478.7 2718.54
   605.7 2796.96   645.4 2813.89   693.9  2847.3   702.7 2858.47     718 2873.76
   799.7 2943.22     813 2952.78   839.4  2967.9   860.6 2976.58   912.6 2991.28
#Mann= 3 ,-1 , 0
       0      .1       0   402.9    .045       0     425      .1       0
Bank Sta=402.9,425
XS Rating Curve= 0 ,0
Exp/Cntr(USF)=0,0
Exp/Cntr=0.3,0.1

Type RM Length L Ch R = 1 ,268     ,287.1,267.6,238
XS GIS Cut Line= 4
2378900.09453203598711.7897975042378821.03429741598416.631588275
2378510.08981628 598226.004442732378244.61913516598221.799176462
#Sta/Elev= 30
       0 2897.96    67.2 2859.77    71.3 2856.83    79.6 2842.39    84.2 2838.04
   133.4 2804.09   174.9 2784.13   187.3 2771.34   305.6 2722.62     388  2715.2
   404.5 2711.48   443.82697.833   453.9 2696.08   465.52697.761   480.1 2703.64
   491.2  2705.3   514.7 2718.12   528.8 2719.22   542.8 2727.37   599.1 2753.02
     632 2763.96   677.6    2783   713.6 2804.87   753.6  2826.2   765.6 2836.52
   781.6 2846.47   789.6 2855.69   817.7 2874.31   857.5 2908.22   935.8 2946.95
#Mann= 3 , 0 , 0
       0      .1       0   443.8    .045       0   465.5      .1       0
Bank Sta=443.8,465.5
XS Rating Curve= 0 ,0
Exp/Cntr(USF)=0,0
Exp/Cntr=0.3,0.1

Type RM Length L Ch R = 1 ,0       ,,,
XS GIS Cut Line= 2
2379194.91581061597912.4027730562378395.52264013598177.921179937
#Sta/Elev= 30
       0 2899.53      46 2911.32    63.4 2913.77    88.7 2914.82   105.6  2914.6
   128.7 2911.47   160.3 2903.05   210.9 2881.47   248.9 2860.44   283.7 2835.18
   303.7 2823.27   316.3 2817.73   366.9 2786.01   403.9 2757.11   422.9 2745.43
   439.3 2739.14   454.6 2731.16     521 2688.52     527 2686.98   548.1 2686.46
     559  2688.5   581.8 2691.24   594.5 2699.63   640.8 2720.09   667.8 2736.53
   708.3 2765.05   734.7 2780.99   777.3 2801.51   817.9 2826.55   842.3 2844.22
#Mann= 4 ,-1 , 0
       0      .1       0   439.3      .1       0     521    .045       0
     559      .1       0
#XS Ineff= 2 , 0
                          566.58         2695.18
Permanent Ineff=
       F       F
Bank Sta=521,559
XS Rating Curve= 0 ,0
Exp/Cntr(USF)=0,0
Exp/Cntr=0.3,0.1
LCMann Table=0

Chan Stop Cuts=-1
Use User Specified Reach Order=0
Composite Channel Slope=5